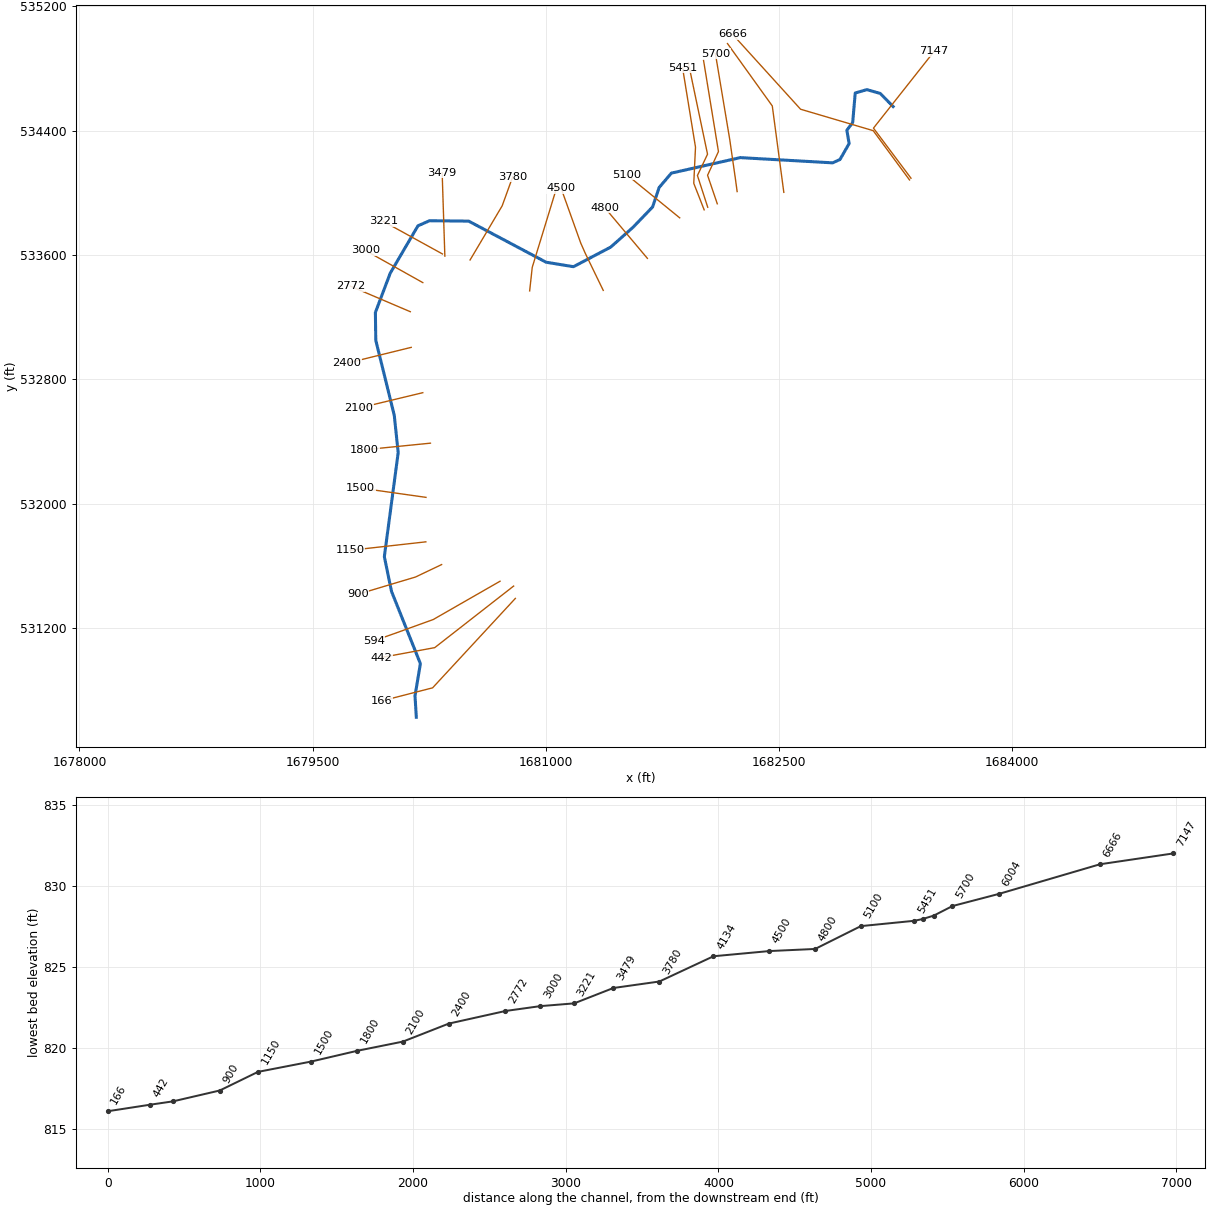
--- EnlowFk.prj (project) ---

Proj Title=EnlowFk
Current Plan=p01
Default Exp/Contr=0,0
English Units
Geom File=g01
Flow File=f01
Plan File=p01
BEGIN DESCRIPTION:
---------- MODELED AS PART OF WVEM CTP PROGRAM, 2025----------
Stream Name: Enlow Fork
Flood Zone: AFH
Marshall County, WV
HEC-RAS Version: RAS 6.6
Vertical Datum: NAVD88
Projection: NAD 1983 StatePlane West Virginia N FIPS 4701 (US Feet)
Terrain: 1-meter West Virginia FEMA R3 South Central (collected 2018-2019)
Land Use: 2024 NLCD
Hydrologic Method:
Duda et al., "Estimation of magnitude and frequency of floods for rural, unregulated streams in and near Virginia and West Virginia." September 8, 2025.
Additional Model Notes:
Coincident peak modeled as normal depth
END DESCRIPTION:
DSS Export Rating Curves= 0
DSS Export Rating Curve Sorted= 0
DSS Export Volume Flow Curves= 0
DXF OffsetX= 0
DXF OffsetY= 0
DXF ScaleX= 0
DXF ScaleY= 0

--- EnlowFk.p01 (plan) ---

Plan Title=Floodplain
Program Version=6.60
Short Identifier=Floodplain
Geom File=g01
Flow File=f01
Subcritical Flow
K Sum by GR= 0
Std Step Tol= 0.01
Critical Tol= 0.01
Num of Std Step Trials= 20
Max Error Tol= 0.3
Flow Tol Ratio= 0.001
Split Flow NTrial= 30
Split Flow Tol= 0.02
Split Flow Ratio= 0.02
Log Output Level= 0
Friction Slope Method= 1
Unsteady Friction Slope Method= 2
Unsteady Bridges Friction Slope Method= 1
Parabolic Critical Depth
Global Vel Dist= 0 , 0 , 0
Global Log Level= 0
CheckData=False
Encroach Param=-1 ,0,0, 0
Flow Ratio Tolerance=0.1
Flow Ratio Min Ratio=0.5
Flow Ratio Max Ratio=4
Flow Ratio Max Iterations= 10
Mapping Interval=1HOUR
Computation Time Step Use Courant=        0
Computation Time Step Use Time Series=    0
Computation Time Step Count To Double=0
Computation Time Step Max Doubling=0
Computation Time Step Max Halving=0
Computation Time Step Residence Courant=0
Run HTab= 0
Run UNet= 0
Run Sediment= 0
Run PostProcess= 0
Run WQNet= 0
Run RASMapper=-1
UNET Theta= 0
UNET Theta Warmup= 0
UNET ZTol= 0
UNET ZSATol= 0
UNET MxIter= 0
UNET Max Iter WO Improvement= 0
UNET MaxInSteps= 0
UNET DtIC= 0
UNET DtMin= 0
UNET MaxCRTS= 0
UNET WFStab= 0
UNET SFStab= 0
UNET WFX= 1
UNET SFX= 1
UNET Gravity=32.17405
UNET 1D Methodology=Finite Difference
UNET DSS MLevel= 1
UNET Pardiso=0
UNET DZMax Abort= 0
UNET Use Existing IB Tables= 0
UNET Froude Reduction=False
UNET Froude Limit= 0
UNET Froude Power= 0
UNET D1 Cores= 0
UNET WindReference=Eulerian
UNET WindDragFormulation=Hsu (1988)
UNET D2 Coriolis=0
UNET D2 Cores= 0
UNET D2 Theta= 1
UNET D2 Theta Warmup= 1
UNET D2 Z Tol= 0.01
UNET D2 Volume Tol= 0.01
UNET D2 Max Iterations= 20
UNET D2 Advanced Convergence=0
UNET D2 WS Max Tol=0.15
UNET D2 WS RMS Tol=0.002
UNET D2 WS Stall Tol=1
UNET D2 Equation= 0
UNET D2 RampUpFraction=0.1
UNET D2 TimeSlices= 1
UNET D2 Turbulence Formulation=Non-Conservative (original)
UNET D2 Eddy Viscosity=0.3
UNET D2 Transverse Eddy Viscosity=0.1
UNET D2 Smagorinsky Mixing=0
UNET D2 BCVolumeCheck=0
UNET D2 Cores=0
UNET D2 SolverType=PARDISO (Direct)
UNET D2 Minimum Iterations= 3
UNET D2 Maximum Iterations= 30
UNET D2 Restart Number= 10
UNET D2 Relaxation Coeff=1.3
UNET D2 SOR Precondition Iterations= 10
UNET D2 ILUT Maximum Fill= 8
UNET D2 ILUT Tolerance=1E-08
UNET D2 Convergence Tolerance=0.00001
PS Theta= 1
PS WS Tol= 0.01
PS Volume Tol= 0.01
PS Max Iterations= 20
PS Equation= 0
PS Advance Time Step=-1
PS Target Courant=0.9
PS Time Slices= 1
PS Iterate With 2D=0
PS Project Initial WSE from DS=-1
PS Ramp Up Initial WSE from US=-1
PS Cores=0
UNET D1D2 MaxIter= 0
UNET D1D2 ZTol=0.01
UNET D1D2 QTol=0.1
UNET D1D2 MinQTol=1
Write IC File= 0
Write IC File at Fixed DateTime=0
Write IC File at Sim End=0
Echo Input=False
Echo Parameters=False
Echo Output=False
Write Detailed= 0
HDF Write Warmup=0
HDF Write Time Slices=0
HDF Flush=0
HDF Compression= 1
HDF Chunk Size= 1
HDF Spatial Parts= 1
HDF Use Max Rows=0
HDF Fixed Rows= 1
Calibration Method= 0
Calibration Iterations= 20
Calibration Max Change=0.05
Calibration Tolerance=0.2
Calibration Maximum=1.5
Calibration Minimum=0.5
Calibration Optimization Method= 1
WQ AD Non Conservative
WQ ULTIMATE=-1
WQ Max Comp Step=1HOUR
WQ Output Interval=15MIN
WQ Output Selected Increments= 0
WQ Create Restart=0
WQ Fixed Restart=0
WQ System Summary=0
WQ Write To DSS=0
Sorting and Armoring Iterations= 10
XS Update Threshold= 0.02
Bed Roughness Predictor= 0
Processes Affected by Predictor=Sediment Only
Hydraulics Update Threshold= 0.02
Energy Slope Method= 1
Volume Change Method= 1
Sediment Retention Method= 0
Sediment TS Multiplier= 1
Warm Up Method= 0
XS Weighting Method= 0
Number of US Weighted Cross Sections= 1
Number of DS Weighted Cross Sections= 1
Upstream XS Weight=0
Main XS Weight=1
Downstream XS Weight=0
Number of DS XS's Weighted with US Boundary= 1
Upstream Boundary Weight= 1
Weight of XSs Associated with US Boundary= 0
Number of US XS's Weighted with DS Boundary= 1
Downstream Boundary Weight= 0.5
Weight of XSs Associated with DS Boundary= 0.5
Percentile Method= 0
Sediment Output Level= 3
Mass or Volume Output= 0
Output Increment Type= 1
Profile and TS Output Increment= 1
Transport Output Increment 1
XS Output Flag= 0
XS Output Increment= 10
Read HDF5 Sediment Hotstart= 0
Sediment Hotstart Type= 0
Write Gradation File= 0
Read Gradation Hotstart= 0
Write HDF5 File= 1
Write Binary Output= 1
Write DSS Sediment File= 0
DSS Sediment Output Type= 1
SV Curve= 0
Specific Gage Flag= 0
Subcell Erosion Methods= 0
Subcell Deposition Methods= 0
Advection Scheme= 1
Matrix Solver= 0
Implicit Weighting Factor= 1
Maximum Outer Loop Convergence Iterations= 5
Convergence Maximum Absolute= 0.001
Convergence RMSE= 0.0001
Grain Fractions Max Abs Error= 0.001
Max Subgrid Regions= 1
Max Subgrid Length Scale= 3.402823E+38
Initial Layer Thickness= 3
Min Layer Thickness= 0.1
Max Layer Thickness= 6
Number of Layers= 5

--- EnlowFk.f01 (steady flow) ---

Flow Title=Flow
Program Version=6.60
Number of Profiles= 1
Profile Names=P100yr
River Rch & RM=EnlowFk,Main,7147
    8950
Boundary for River Rch & Prof#=EnlowFk,Main            , 1
Up Type= 0
Dn Type= 3
Dn Slope=0.005199
DSS Import GetInterval= 0
DSS Import GetPeak= 0
DSS Import FillOption= 0

--- EnlowFk.g01 (geometry) ---

Geom Title=Geometry
Program Version=6.60

River Reach=EnlowFk         ,Main
Reach XY= 30
1683233.60441816534555.7304311771683150.54851211534640.067103411
1683064.82590362534664.4817703861682989.95425823534642.779844186
1682973.52565297534452.5367073861682935.93780164534403.098814145
1682950.83212881534317.7590898131682891.78369047534214.959098563
1682844.61022839534193.5736426411682250.46213847534227.103103146
1681807.19891739534127.354943067 1681728.5255183534034.592333317
1681686.66175689533909.9045905621681560.86607672533779.077096313
1681417.13211222 533651.54552722 1681177.6171713533525.548731983
1681001.82257539533554.2176378971680503.55388689533818.703001305
 1680251.5875273 533821.161657811680177.39016914  533788.6797674
 1679999.1136228533484.0865445581679903.50882713533231.237312734
1679906.02489822533051.9784848991680024.94099897532569.473872483
1680050.12467563532329.4917408971679961.06022123531659.974051058
1680007.12804247531437.3134071381680192.99610905530972.459349975
1680158.37085022530765.2911291421680166.68907505530627.635236472

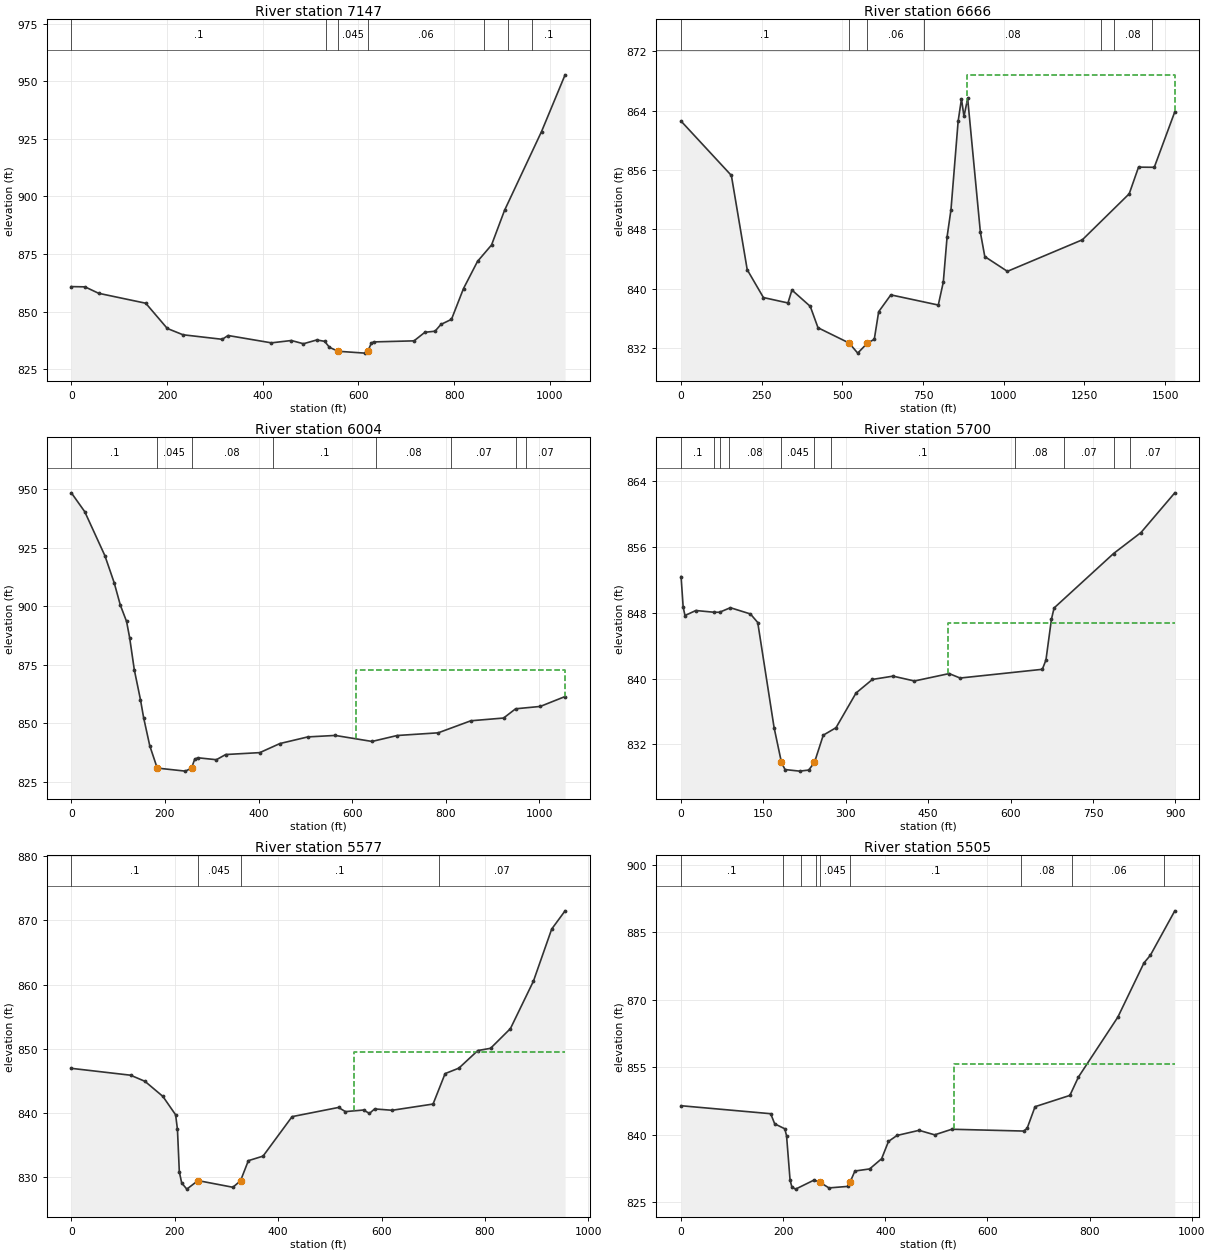
Type RM Length L Ch R = 1 ,7147    ,421.8,481.1,536.2
XS GIS Cut Line= 3
1683348.61613731534094.6507991161683107.22234528534416.902802135
1683497.48784558534910.557061715
#Sta/Elev= 30
       0  860.88    28.4  860.77    57.1  857.97   155.5  853.66   200.5  842.71
   233.3  839.97   315.3     838   327.6  839.65   418.1  836.46   459.9  837.48
     485  836.07     513  837.72   529.4  837.12   539.4  834.53   557.4  832.81
   613.5     832  619.43   832.8   627.2  836.42   632.2  836.87   716.2  837.33
   738.9  841.05   760.1  841.51   772.3  844.44   794.5  846.68   819.6  860.04
   848.9  871.83   878.2  878.94   905.4  893.99   982.7   928.2  1031.9  952.81
#Mann= 7 ,-1,0
       0      .1       0  532.64     .06       0   557.4    .045       0
  619.43     .06       0  862.64      .1       0  912.64     .05       0
  962.64      .1       0
Bank Sta=557.4,619.43
XS Rating Curve= 0 ,0
Exp/Cntr(USF)=0,0
Exp/Cntr=0.3,0.1

Type RM Length L Ch R = 1 ,6666    ,677.2,662,604.6
XS GIS Cut Line= 4
1683339.14995374534083.5815136931683105.68488682534400.495981459
1682638.41663653534538.4395340691682201.94480166 535019.17982498
#Sta/Elev= 30
       0  862.59   155.9  855.27     205  842.57   255.2  838.82   331.3  838.09
   343.6  839.83   400.4  837.63   424.4  834.75  520.74832.6937   547.5  831.33
  577.78 832.694   598.8  833.19   612.4  836.91   650.1  839.18   797.2  837.81
   812.7   840.9   824.5  847.02   836.5  850.65   858.7  862.57     869  865.59
   876.8  863.23   888.2  865.65   927.7  847.59   941.3  844.34  1011.4  842.35
  1243.6   846.6  1388.9   852.8  1417.8  856.39  1466.6  856.37  1530.2  863.85
#Mann= 7 ,-1,0
       0      .1       0  520.74    .045       0  577.78     .06       0
  753.63     .08       0 1300.83     .07       0 1340.83     .08       0
 1460.83     .06       0
#XS Ineff= 2 , 0
                          884.91          868.83
Permanent Ineff=
       F       F
Bank Sta=520.74,577.78
XS Rating Curve= 0 ,0
Exp/Cntr(USF)=0,0
Exp/Cntr=0.3,0.1

Type RM Length L Ch R = 1 ,6004    ,302.5,304.3,301.3
XS GIS Cut Line= 3
 1682530.6190585534003.7285499271682456.40280384534559.551834687
1682168.19010545534960.886457167
#Sta/Elev= 30
       0  948.49    28.6  940.43    71.6  921.64    91.5  910.06   104.7  900.45
     118  893.48   124.6  886.48   134.5  872.84   147.7  860.02   154.4  852.37
   167.6  840.31  183.46 830.803   243.7   829.5  256.73 830.803   263.6  834.61
   270.2  835.21   309.9  834.38   329.8   836.6   402.6  837.41   445.6  841.29
   505.2  844.13   563.8  844.76   642.4  842.19   696.1  844.73   783.8  845.88
   853.6  851.03   923.5   852.2   949.2  856.15  1001.9  857.16  1054.9  861.39
#Mann= 8 ,-1,0
       0      .1       0  183.46    .045       0  256.73     .08       0
     430      .1       0  650.76     .08       0  810.76     .07       0
  950.76     .08       0  970.76     .07       0
#XS Ineff= 2 , 0
                          607.12          872.77
Permanent Ineff=
       F       F
Bank Sta=183.46,256.73
XS Rating Curve= 0 ,0
Exp/Cntr(USF)=0,0
Exp/Cntr=0.3,0.1

Type RM Length L Ch R = 1 ,5700    ,146.7,122.6,101.7
XS GIS Cut Line= 6
1682230.37490834 534008.664891751682218.56128368534095.366161928
1682207.86314234534169.5992811771682193.59545434534268.576445416
1682182.89665684534342.8092365861682090.43798042534896.631285464
#Sta/Elev= 30
       0  852.41     3.8   848.7     7.1  847.67    26.9  848.28      60  848.07
      70  848.07    89.8  848.62   126.3  847.86   139.6  846.82   169.4  834.03
  182.78829.8076   189.3  828.94   215.8  828.75   232.4  828.88  242.86829.8069
   258.9  833.12   282.1  834.03   318.6  838.25   348.4   839.9   385.9   840.3
   424.9  839.71   488.1  840.61   508.1  840.07   657.8  841.13   664.4  842.27
   674.4  847.23   679.2  848.59   787.5  855.21   837.4  857.76     899  862.59
#Mann= 11 ,-1,0
       0      .1       0      60     .08       0      70      .1       0
    87.5     .08       0  182.78    .045       0  242.86     .08       0
   272.5      .1       0   607.5     .08       0   697.5     .07       0
   787.5     .08       0   817.5     .07       0
#XS Ineff= 2 , 0
                          486.72          846.73
Permanent Ineff=
       F       F
Bank Sta=182.78,242.86
XS Rating Curve= 0 ,0
Exp/Cntr(USF)=0,0
Exp/Cntr=0.3,0.1

Type RM Length L Ch R = 1 ,5577    ,62.4,72.3,73.3
XS GIS Cut Line= 4
1682102.63652809533930.1260562111682040.20617002  534113.4373586
1682110.13977191534266.2953212491682014.45810176534851.564461558
#Sta/Elev= 30
       0  846.97   114.6   845.9   142.3  844.95     177   842.6   201.6  839.74
   205.2  837.45   208.8  830.85   213.4  829.12   223.3  828.16   244.9  829.49
   312.4  828.45  327.14  829.46   342.3  832.59   370.7   833.3   426.9  839.45
   516.7  840.88     530  840.23     565  840.48   576.5  839.95   586.5  840.65
   620.4  840.44   699.5  841.41   722.8  846.15   749.4     847     786  849.74
   810.7  850.09   849.1  853.16   893.6  860.55   928.9  868.66   954.8   871.5
#Mann= 4 ,-1,0
       0      .1       0   244.9    .045       0  327.14      .1       0
  711.75     .07       0
#XS Ineff= 2 , 0
                          546.07          849.54
Permanent Ineff=
       F       F
Bank Sta=244.9,327.14
XS Rating Curve= 0 ,0
Exp/Cntr(USF)=0,0
Exp/Cntr=0.3,0.1

Type RM Length L Ch R = 1 ,5505    ,45.6,54.2,68.9
XS GIS Cut Line= 4
1682041.23154346533907.7206148391681974.95235903534112.081433522
 1682039.8626439534249.0322255971681916.55273012534836.813024419
#Sta/Elev= 30
       0  846.46   175.5  844.69   183.4  842.44   203.2  841.34   206.6  839.78
   213.5  829.94   217.1   828.4   224.3  827.95   260.6  829.97   271.5  829.49
   289.7  828.22     326  828.55  330.95   829.5   340.5  831.97   369.3  832.43
   392.8   834.7   406.2  838.54   422.9  839.86   466.1     841   496.7     840
   530.2  841.24   671.1  840.84   677.7  841.43   693.3  846.25   761.5  848.75
   778.3  852.84   855.4  866.12   906.6  878.16   919.1  879.85     967  889.72
#Mann= 9 ,-1,0
       0      .1       0     200     .08       0  234.84      .1       0
  264.84     .03       0   271.5    .045       0  330.95      .1       0
  666.39     .08       0  766.39     .06       0  946.39      .1       0
#XS Ineff= 2 , 0
                          533.63           855.8
Permanent Ineff=
       F       F
Bank Sta=271.5,330.95
XS Rating Curve= 0 ,0
Exp/Cntr(USF)=0,0
Exp/Cntr=0.3,0.1

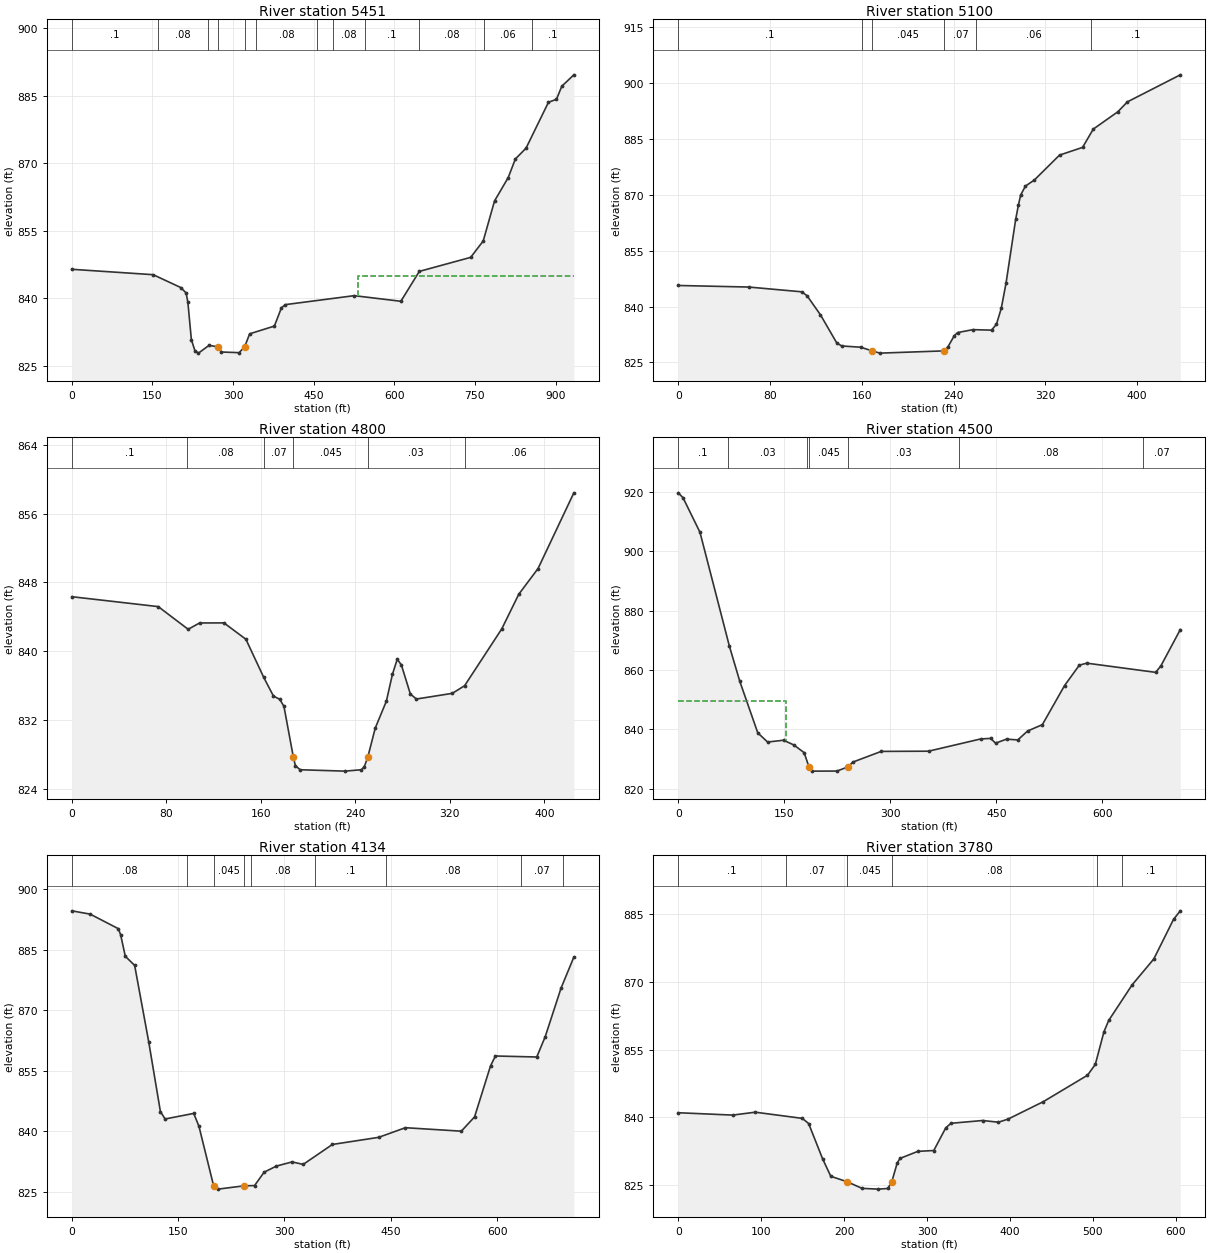
Type RM Length L Ch R = 1 ,5451    ,329.8,351.3,374.4
XS GIS Cut Line= 4
1682018.32721665533891.1244571131681951.34589253534061.934502566
1681962.52311782534294.2506962811681879.23489133534805.480657024
#Sta/Elev= 30
       0  846.47   151.4  845.27   202.8  842.41   212.7  841.21     216  839.12
   222.5  830.82   229.1  828.37   235.7  827.84   255.4  829.57   271.8  829.24
   278.4  828.09   311.3  827.94  321.65  829.25   330.9  832.13   376.9  833.85
   390.1  837.93   397.5  838.62   525.5  840.61   612.2  839.36   646.5     846
   742.1  849.12   765.4  852.76   786.5  861.67   811.9  866.85   825.2  870.98
   845.1  873.39   886.8  883.59   901.7  884.24   911.6  887.15     934  889.68
#Mann= 12 ,-1,0
       0      .1       0     160     .08       0  253.47     .03       0
   271.8    .045       0  321.65     .03       0  343.47     .08       0
  456.06      .1       0  486.06     .08       0  546.06      .1       0
  646.06     .08       0  766.06     .06       0  856.06      .1       0
#XS Ineff= 2 , 0
                          532.13          844.93
Permanent Ineff=
       F       F
Bank Sta=271.8,321.65
XS Rating Curve= 0 ,0
Exp/Cntr(USF)=0,0
Exp/Cntr=0.3,0.1

Type RM Length L Ch R = 1 ,5100    ,303,299.7,292.8
XS GIS Cut Line= 2
1681860.86462537533839.7382823151681521.54610566534116.175568388
#Sta/Elev= 30
       0  845.66    61.5  845.24   107.7  843.96   112.3  842.91     124  837.78
   138.3  830.19   142.6  829.43   158.9   829.1  169.19 828.115   175.8  827.51
  231.98 828.116     235  829.13   240.6  832.15   243.5  833.02   256.9  833.81
   273.1  833.68   277.4  835.24   281.6  839.51   285.8  846.33   294.2  863.45
   296.5  867.13   298.5  869.93   302.7  872.33   310.5  873.97   332.4  880.64
   352.5  882.71   361.8  887.61   383.2  892.26   391.6  894.93   437.7  902.18
#Mann= 6 ,-1,0
       0      .1       0     160     .07       0  169.19    .045       0
  231.98     .07       0     260     .06       0     360      .1       0
Bank Sta=169.19,231.98
XS Rating Curve= 0 ,0
Exp/Cntr(USF)=0,0
Exp/Cntr=0.3,0.1

Type RM Length L Ch R = 1 ,4800    ,306.4,300,292.2
XS GIS Cut Line= 6
1681653.15591842533579.0381263351681596.84074233533646.007152513
1681548.57082576533703.4095967561681484.21071826533779.945532918
1681435.94112976533837.3479771761681379.62595367 533904.31700334
#Sta/Elev= 30
       0  846.35    73.2   845.2    98.5  842.57   108.2   843.3   128.8  843.31
   147.4  841.41   162.5  836.98   170.7  834.82   176.1  834.43   179.6  833.62
   187.6827.6975   189.3  826.73   193.3  826.26   231.3   826.1   245.2  826.26
   247.6  826.61  250.53827.7007   256.9   831.1   266.3  834.22   271.4  837.32
   275.5  839.09     279  838.43   286.6  835.06   291.7  834.47   322.1  835.13
   332.5  836.01     364  842.62   378.4  846.64   394.7  849.62     425  858.41
#Mann= 6 ,-1,0
       0      .1       0    97.5     .08       0   162.5     .07       0
   187.6    .045       0  250.53     .03       0   332.5     .06       0
Bank Sta=187.6,250.53
XS Rating Curve= 0 ,0
Exp/Cntr(USF)=0,0
Exp/Cntr=0.3,0.1

Type RM Length L Ch R = 1 ,4500    ,384.4,365.5,345.5
XS GIS Cut Line= 6
1681369.08102725533373.144181177  1681330.906891533451.877947584
1681298.18648401533519.3640330881681254.55927467533609.345480427
  1681224.194506533677.9739520851681098.52705396534028.698671339
#Sta/Elev= 30
       0  919.64     6.7  918.02    30.7  906.39    72.3  868.07    87.1  856.16
   112.5  838.85   126.4  835.76   148.9  836.37   163.5  834.78   178.1  832.18
   184.8 827.465     189  825.97   224.6  825.99  240.66827.4679   246.7  828.99
   287.1  832.61     354  832.68   427.9  836.81   441.8  836.98   448.9  835.38
   464.3  836.74   480.2  836.47   494.1  839.47     515  841.61   546.4  854.77
   567.3  861.64   577.8  862.31   675.3  859.21   682.7  861.42   710.1  873.62
#Mann= 7 ,-1,0
       0      .1       0      70     .03       0   182.5      .1       0
   184.8    .045       0  240.66     .03       0  397.55     .08       0
  657.55     .07       0
#XS Ineff= 2 , 0
          151.91  849.47
Permanent Ineff=
       F       F
Bank Sta=184.8,240.66
XS Rating Curve= 0 ,0
Exp/Cntr(USF)=0,0
Exp/Cntr=0.3,0.1

Type RM Length L Ch R = 1 ,4134    ,359.2,354.6,349.2
XS GIS Cut Line= 3
1680895.73387684  533369.73605151680912.46395648533521.704169384
1681075.20654772534052.561425577
#Sta/Elev= 30
       0  894.61      26  893.79    65.6  890.19    68.9  888.69    75.5  883.35
    88.7  881.08   108.5  862.17     125  844.88   131.6  843.03     172  844.41
   179.4   841.2  200.05826.4785   206.3  825.65  243.21826.4766   257.8  826.53
   271.3  829.85   288.6  831.36   310.7  832.39   326.4  831.78   367.6  836.72
   432.8  838.48   470.5  840.87   549.4  840.01   568.1  843.56   590.6  856.19
   597.5  858.64   655.8  858.39   667.7  863.41   690.1  875.48   708.1  883.14
#Mann= 9 ,-1,0
       0     .08       0  162.89     .07       0  200.05    .045       0
  243.21     .07       0  252.89     .08       0  342.89      .1       0
  442.89     .08       0  632.89     .07       0  692.89     .06       0
Bank Sta=200.05,243.21
XS Rating Curve= 0 ,0
Exp/Cntr(USF)=0,0
Exp/Cntr=0.3,0.1

Type RM Length L Ch R = 1 ,3780    ,286.4,301.2,314.3
XS GIS Cut Line= 3
1680512.55138966533568.7236987221680719.10019177533917.317974924
1680787.34826522534105.461795246
#Sta/Elev= 30
       0  841.02    65.7   840.5    92.9  841.14   149.6  839.77   157.2  838.63
     174  830.83   183.9  826.94   203.8  825.71   221.6  824.26   241.1  824.09
   252.6  824.23  257.46  825.72     264  829.89   267.4   830.9   288.9  832.46
   308.1  832.65   322.5  837.66   328.8  838.68     367   839.3     386  838.92
   397.5   839.6     440  843.46   493.4  849.33   502.8  851.72   513.3     859
     519  861.48   547.2  869.36   573.3  875.09   597.1  883.87   605.3  885.77
#Mann= 6 ,-1,0
       0      .1       0     130     .07       0   203.8    .045       0
  257.46     .08       0  505.19     .07       0  535.19      .1       0
Bank Sta=203.8,257.46
XS Rating Curve= 0 ,0
Exp/Cntr(USF)=0,0
Exp/Cntr=0.3,0.1

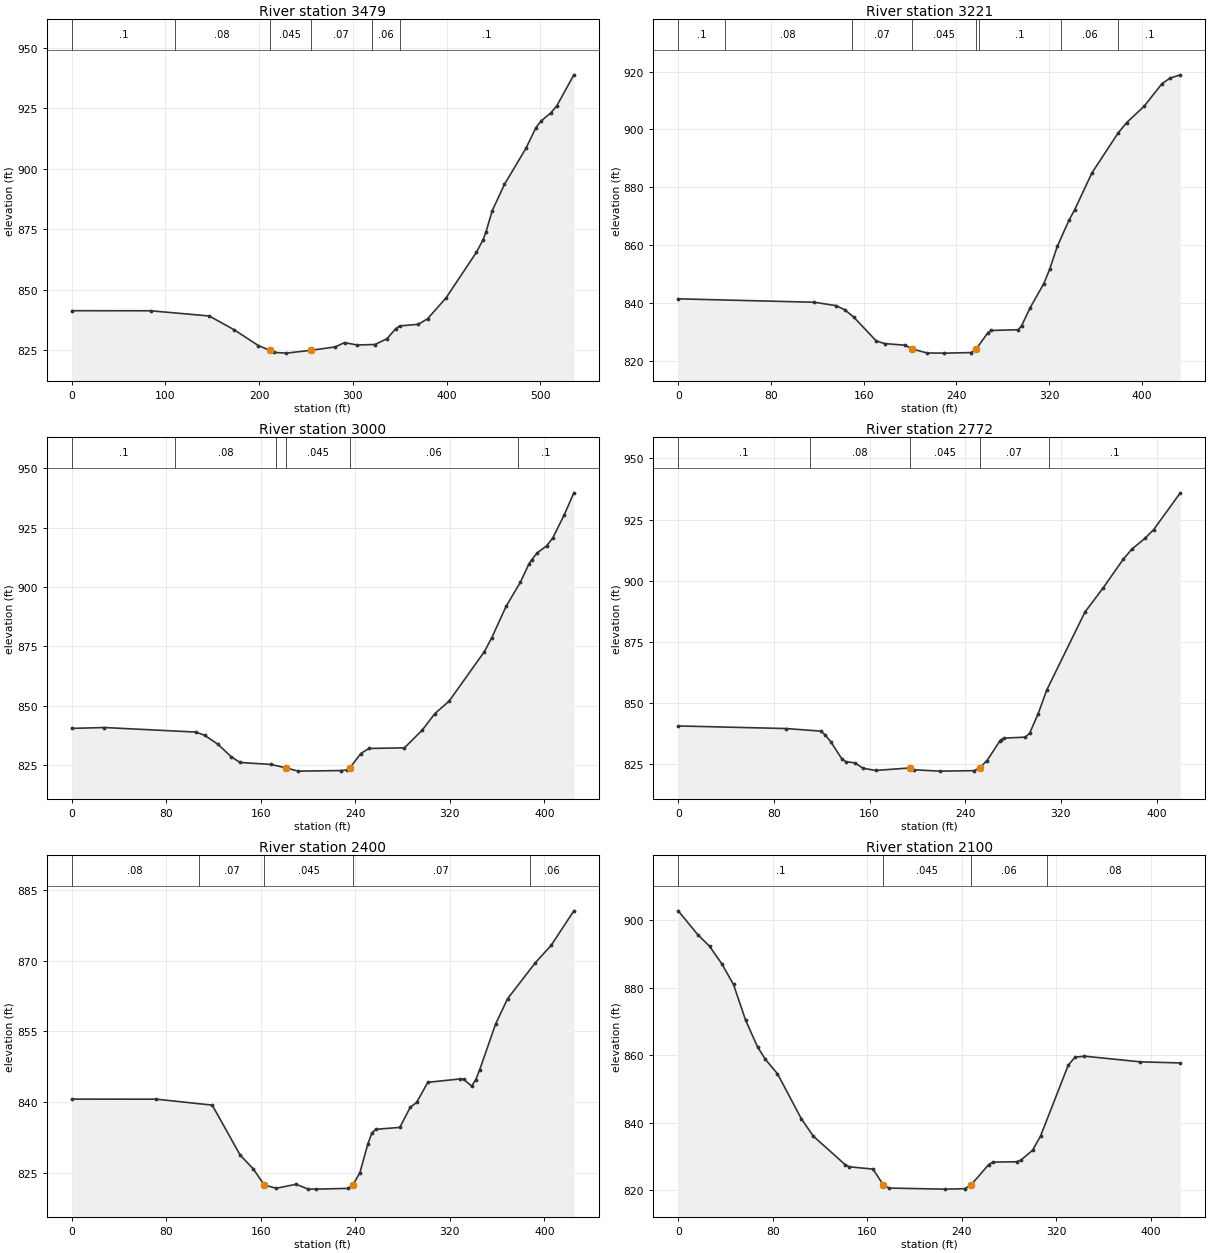
Type RM Length L Ch R = 1 ,3479    ,233.3,257.2,285
XS GIS Cut Line= 2
1680350.29632589533593.5220685841680333.03141677534129.000706758
#Sta/Elev= 30
       0  841.25    84.3  841.22   146.6  839.07   172.9  833.45   199.1  826.83
  211.25 824.837   215.6     824   228.7  823.69  254.95824.8375   281.2  826.27
   291.1  828.05   304.2  827.06   323.7  827.26   336.4  829.67   345.9  833.86
   350.1  834.96   369.8  835.62   379.7  837.91   399.4  846.54   431.8  865.42
   438.8  870.48   442.1  873.91   448.6  882.53   461.7   893.5   484.7  908.48
   495.4  917.06   501.1  919.88     511  923.02   517.6  926.01   535.8  938.87
#Mann= 6 ,-1,0
       0      .1       0     110     .08       0  211.25    .045       0
  254.95     .07       0     320     .06       0     350      .1       0
Bank Sta=211.25,254.95
XS Rating Curve= 0 ,0
Exp/Cntr(USF)=0,0
Exp/Cntr=0.3,0.1

Type RM Length L Ch R = 1 ,3221    ,221.2,221.5,220.8
XS GIS Cut Line= 2
  1680334.692941 533607.581106591679955.04082284 533816.58422209
#Sta/Elev= 30
       0   841.5   117.4  840.31   136.2  839.15   143.7  837.73   151.6  835.15
   170.9  826.97   178.1  826.04   196.1  825.46  201.72824.2188   214.8  822.79
   229.8  822.74     253  822.94  257.38824.2224   267.2  829.77   269.9  830.56
   293.5  830.83   296.5  832.28   303.7  838.36   315.6  846.79   320.6   851.7
   327.2  859.61   337.5  868.83   342.2  872.24   357.1  884.99   379.6  898.72
   387.1  902.38   402.1  907.99   417.6  915.83   424.5  917.72   433.4  918.87
#Mann= 8 ,-1,0
       0      .1       0      40     .08       0     150     .07       0
  201.72    .045       0  257.38     .07       0     260      .1       0
     330     .06       0     380      .1       0
Bank Sta=201.72,257.38
XS Rating Curve= 0 ,0
Exp/Cntr(USF)=0,0
Exp/Cntr=0.3,0.1

Type RM Length L Ch R = 1 ,3000    ,224.3,228.2,230.3
XS GIS Cut Line= 6
1680208.54627484533423.1969025881680132.18651943533465.922210842
1680066.73487867533502.5432005821679979.46668051533551.371843085
1679914.01536784533587.9931609181679837.65528435533630.718141094
#Sta/Elev= 30
       0  840.55    27.7  840.91   104.9     839   112.4  837.65   123.7  833.88
     135  828.59   142.5  826.21   168.8  825.37  181.57823.9136   191.6  822.57
   227.8  822.81   232.6  823.01  235.37823.9131   244.7  829.98   251.5  832.11
   281.6  832.36   296.7  839.85   307.3  846.74   319.4     852   349.3  872.86
   355.6  878.77   367.6  891.83   379.7     902   386.8  909.53   389.3  911.49
   394.1   914.4   401.9  917.29   407.1  920.61     417  930.51     425  939.63
#Mann= 6 ,-1,0
       0      .1       0    87.5     .08       0   172.5     .06       0
  181.57    .045       0  235.37     .06       0   377.5      .1       0
Bank Sta=181.57,235.37
XS Rating Curve= 0 ,0
Exp/Cntr(USF)=0,0
Exp/Cntr=0.3,0.1

Type RM Length L Ch R = 1 ,2772    ,351.3,371.8,391.6
XS GIS Cut Line= 2
1680128.07012406533236.0112382811679741.87321129533400.805450808
#Sta/Elev= 30
       0  840.72    90.5  839.65   119.1   838.6   122.6  837.22   127.6  834.26
   136.9  827.23   140.1  826.15   147.6  825.65   154.7  823.42   165.1  822.55
     194  823.58   197.5  822.81   218.9  822.27   247.5  822.47  251.98823.5613
   258.2  826.55   268.9  834.53   270.1     835   272.4  835.75   290.3  836.14
   293.9  837.76     301  845.69   308.1  855.28   340.2  887.26   355.1  896.89
   372.3  908.87   379.5  912.96   390.2  917.25   397.6  920.87   419.9  935.89
#Mann= 5 ,-1,0
       0      .1       0     110     .08       0     194    .045       0
  251.98     .07       0     310      .1       0
Bank Sta=194,251.98
XS Rating Curve= 0 ,0
Exp/Cntr(USF)=0,0
Exp/Cntr=0.3,0.1

Type RM Length L Ch R = 1 ,2400    ,300.2,300,299.8
XS GIS Cut Line= 6
1680134.02575459 533006.695767091680049.06168567532985.781766921
1679976.23571584532967.854965508  1679879.134204532943.952782333
1679806.30823417532926.0263089981679721.34449334532905.112308845
#Sta/Elev= 30
       0  840.61    71.6   840.6   118.9  839.34   142.6   828.7   153.6   825.8
  162.96822.3846     173  821.67   189.9  822.52     200   821.5   206.8  821.49
   233.8  821.65  237.99822.3862   243.9     825   250.7  831.15   254.1  833.45
   257.4   834.2   277.7  834.61   286.5  838.88   291.9  839.91   301.4  844.19
   328.4  844.89   331.8  844.81   338.5  843.38   341.9  844.71   345.3  846.86
   358.8  856.59   368.9  861.94   392.2  869.53   405.8  873.29     425  880.62
#Mann= 5 ,-1,0
       0     .08       0   107.5     .07       0  162.96    .045       0
  237.99     .07       0   387.5     .06       0
Bank Sta=162.96,237.99
XS Rating Curve= 0 ,0
Exp/Cntr(USF)=0,0
Exp/Cntr=0.3,0.1

Type RM Length L Ch R = 1 ,2100    ,305,300,294.9
XS GIS Cut Line= 6
1680208.44096009 532715.153371171680123.37124833532694.673425257
 1680050.4547275532677.119326502  1679953.232481 532653.71386151
1679880.31563209532636.1597627551679795.24592035532615.679816842
#Sta/Elev= 30
       0  902.78    16.5  895.74    26.6  892.25    36.7  887.18    46.8  880.97
      57  870.43    67.1  862.52    73.8  858.79      84  854.54   104.2  841.22
   114.3  836.08   141.3  827.63   144.7     827   164.9  826.31  173.67821.5768
   178.4  820.69   225.7  820.38   242.6  820.51  247.75 821.579   262.8  827.65
   266.2  828.38   286.4  828.49   289.8   828.9   299.9  831.87   306.7  836.11
   330.1  857.05   335.8  859.44   343.8  859.75     391  858.07     425  857.74
#Mann= 4 ,-1,0
       0      .1       0  173.67    .045       0  247.75     .06       0
   312.5     .08       0
Bank Sta=173.67,247.75
XS Rating Curve= 0 ,0
Exp/Cntr(USF)=0,0
Exp/Cntr=0.3,0.1

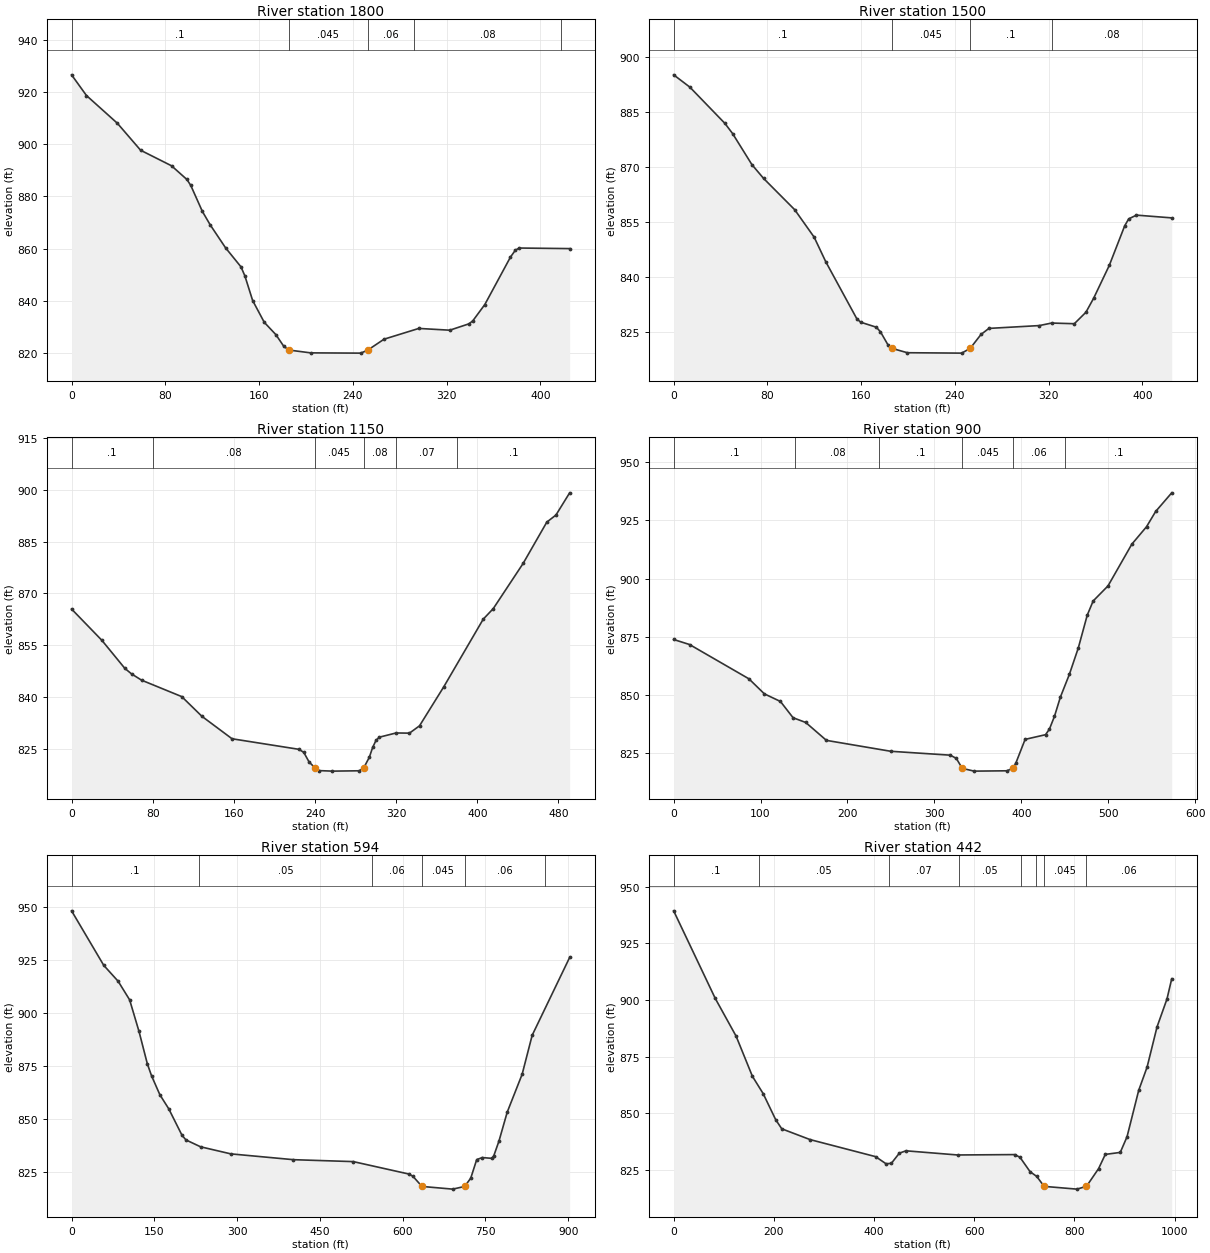
Type RM Length L Ch R = 1 ,1800    ,306.4,300,290.1
XS GIS Cut Line= 6
1680257.58882767532390.435844749  1680170.523385 532381.72621651
1680095.89558151532374.2610083371679996.39249967532364.306960002
1679921.76469618 532356.841423751679834.69925351532348.131795511
#Sta/Elev= 30
       0  926.74    12.7  918.79    39.1  908.12    58.9  897.77    85.3  891.79
    98.4  886.53   101.7  884.26   111.6  874.26   118.3  869.09   131.4  860.27
   144.6  852.93   147.9  849.46   154.5  840.03   164.4  831.66   174.3  826.93
   180.9  822.55  185.15821.0102     204  819.91   246.8  819.81  252.86821.0095
   266.6  825.16   296.3   829.3   322.7  828.62   339.1  831.07   342.4  832.24
   352.6  838.47   374.5  856.72   378.7  859.37     382  860.19     425  859.97
#Mann= 5 ,-1,0
       0      .1       0  185.15    .045       0  252.86     .06       0
   292.5     .08       0   417.5      .1       0
Bank Sta=185.15,252.86
XS Rating Curve= 0 ,0
Exp/Cntr(USF)=0,0
Exp/Cntr=0.3,0.1

Type RM Length L Ch R = 1 ,1500    ,343.6,349.6,355.6
XS GIS Cut Line= 6
1680229.09643058532041.8699408321680142.45946476532054.129758835
1680068.19944267532064.6382680091679969.18586117 532078.64939484
  1679894.925511532089.1579039991679808.28854518532101.417722002
#Sta/Elev= 30
       0  895.12    13.8  891.77    43.7  881.88    50.3  879.09    66.8   870.6
    76.8  866.82   103.3   858.3   119.9   850.8   129.8   844.1   156.3  828.53
   159.6  827.59   172.9  826.23   176.5  824.96   182.8  821.45  186.26820.4491
   199.4  819.26   245.8  819.15  253.04820.4507   262.3  824.26     269   825.9
     312  826.67   322.5  827.36   341.9  827.18   351.8  830.31   358.4  834.15
   371.7  843.08   384.9  853.92   388.3   855.8   394.9  856.82     425  856.07
#Mann= 4 ,-1,0
       0      .1       0  186.26    .045       0  253.04      .1       0
   322.5     .08       0
Bank Sta=186.26,253.04
XS Rating Curve= 0 ,0
Exp/Cntr(USF)=0,0
Exp/Cntr=0.3,0.1

Type RM Length L Ch R = 1 ,1150    ,245.2,250.4,255.5
XS GIS Cut Line= 2
1680228.23644805531755.7657717661679740.26763935531701.191598409
#Sta/Elev= 30
       0  865.45    29.9  856.38    52.5  848.27    59.1  846.67      69  844.85
   108.6  840.09   128.5  834.38   158.2  827.88   224.2  824.82   228.9  823.94
   234.1  821.18  240.09819.4116     244  818.66   257.2  818.51   283.6  818.61
  287.94819.4131   293.5  822.51   296.8  825.36   300.1  827.41   303.4  828.34
   319.9  829.56   333.1  829.51     343  831.63     367  842.97   405.8  862.51
   415.7  865.57   445.1  878.64   468.5  890.62   477.5  892.67     491   899.1
#Mann= 6 ,-1,0
       0      .1       0      80     .08       0  240.09    .045       0
  287.94     .08       0     320     .07       0     380      .1       0
Bank Sta=240.09,287.94
XS Rating Curve= 0 ,0
Exp/Cntr(USF)=0,0
Exp/Cntr=0.3,0.1

Type RM Length L Ch R = 1 ,900     ,305.1,306,307.5
XS GIS Cut Line= 6
1680329.63639964531609.5585240941680161.13299873531529.277582263
1680042.34811643 531493.918280841679946.56549959531465.183430165
1679874.72870101 531443.632620261679790.91882926531418.489625916
#Sta/Elev= 30
       0  873.87    18.3  871.71    86.6  856.99   104.4  850.53   122.9  847.26
   137.4  840.29     152  838.24   175.8  830.56   249.8  825.88   318.3  824.21
   325.2  822.85  332.08818.5508   345.7  817.36   383.4   817.5  390.29818.5499
   393.7  820.76   404.4  830.99   427.9     833   432.4  835.41   438.2  840.89
     445  849.14   455.3  858.87   465.6  870.22   475.9  884.32   482.7   890.4
   499.8  896.88   527.2  914.79   544.1  922.27   554.6  928.82   573.1  936.83
#Mann= 6 ,-1,0
       0      .1       0     140     .08       0  236.65      .1       0
  332.08    .045       0  390.29     .06       0  450.59      .1       0
Bank Sta=332.08,390.29
XS Rating Curve= 0 ,0
Exp/Cntr(USF)=0,0
Exp/Cntr=0.3,0.1

Type RM Length L Ch R = 1 ,594     ,158,152.3,144.9
XS GIS Cut Line= 4
1680705.27950126531502.3819756641680275.78311178531256.122817053
1680037.51906039531169.976959524 1679892.1745348 531118.78422611
#Sta/Elev= 30
       0  948.07    58.3  922.34    84.4  914.82   105.2  906.05   122.2  891.13
   137.3  875.84   144.9   870.2     160  861.24   176.1   854.6   200.1  842.11
   207.3  839.91   233.8  836.67   288.6  833.33     402  830.59   510.5  829.68
   611.6  823.79   618.6  822.73  634.91817.9576   690.6  816.69  712.29817.9574
   723.3  821.87   734.1  830.64   744.2  831.59   761.6  831.22   765.1  832.47
   774.4  839.36   789.4  853.05   816.4   870.9   834.6  889.32   902.5  926.06
#Mann= 6 ,-1,0
       0      .1       0     230     .05       0  545.09     .06       0
  634.91    .045       0  712.29     .06       0  858.45      .1       0
Bank Sta=634.91,712.29
XS Rating Curve= 0 ,0
Exp/Cntr(USF)=0,0
Exp/Cntr=0.3,0.1

Type RM Length L Ch R = 1 ,442     ,262.9,275.2,278.4
XS GIS Cut Line= 3
1680792.68426617531471.3156264341680285.08103351531075.230519562
1679940.65385628531011.614968559
#Sta/Elev= 30
       0  939.36    83.1  900.66   124.7  884.01   157.2   866.3   178.7  858.64
   203.7  847.13   215.8  843.11   272.2  838.36   403.1  830.82   423.8  827.69
   434.5  827.86   450.5  832.37   463.8   833.4   566.7  831.56   681.3  831.73
   691.4  830.49   711.4  824.18   724.7  822.08  739.51817.6952   804.8  816.48
  823.92817.6967   848.2  825.56   861.5  831.81   891.4  832.69   904.9   839.6
   928.2   860.1   944.9  870.33   964.8  888.12   984.6  900.41   994.1  909.37
#Mann= 8 ,-1,0
       0      .1       0     170     .05       0     430     .07       0
     570     .05       0  693.85     .07       0  723.85      .1       0
  739.51    .045       0  823.92     .06       0
Bank Sta=739.51,823.92
XS Rating Curve= 0 ,0
Exp/Cntr(USF)=0,0
Exp/Cntr=0.3,0.1

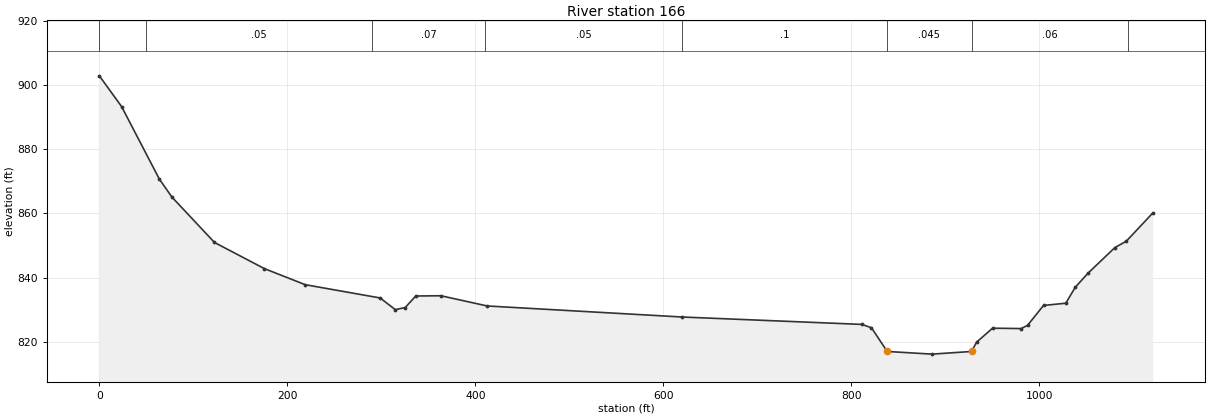
Type RM Length L Ch R = 1 ,166     ,,,
XS GIS Cut Line= 3
1680803.84352428531392.0058082381680271.46211225530816.665665552
1679945.35079582530732.793858084
#Sta/Elev= 30
       0  902.99    23.7  893.38    63.9  870.71    77.3   865.1   122.5  850.95
   175.6  842.78   219.1  837.76   298.7  833.62   314.9  829.96   325.4  830.64
   336.6  834.23   363.4  834.31   412.6  831.12     620  827.67   811.3  825.36
   821.4  824.31  838.12816.9108   885.8  816.08  927.87 816.909   933.2  819.81
   950.2  824.18   980.6  824.06   987.4  825.06  1004.4  831.28  1028.1  831.98
  1038.2  836.97  1051.8  841.37  1080.3  849.35  1092.4  851.32  1120.6  860.14
#Mann= 8 ,-1,0
       0      .1       0      50     .05       0     290     .07       0
     410     .05       0     620      .1       0  838.12    .045       0
  927.87     .06       0 1093.87      .1       0
Bank Sta=838.12,927.87
XS Rating Curve= 0 ,0
Exp/Cntr(USF)=0,0
Exp/Cntr=0.3,0.1
LCMann Table=0

Chan Stop Cuts=-1
Use User Specified Reach Order=0
Composite Channel Slope=5